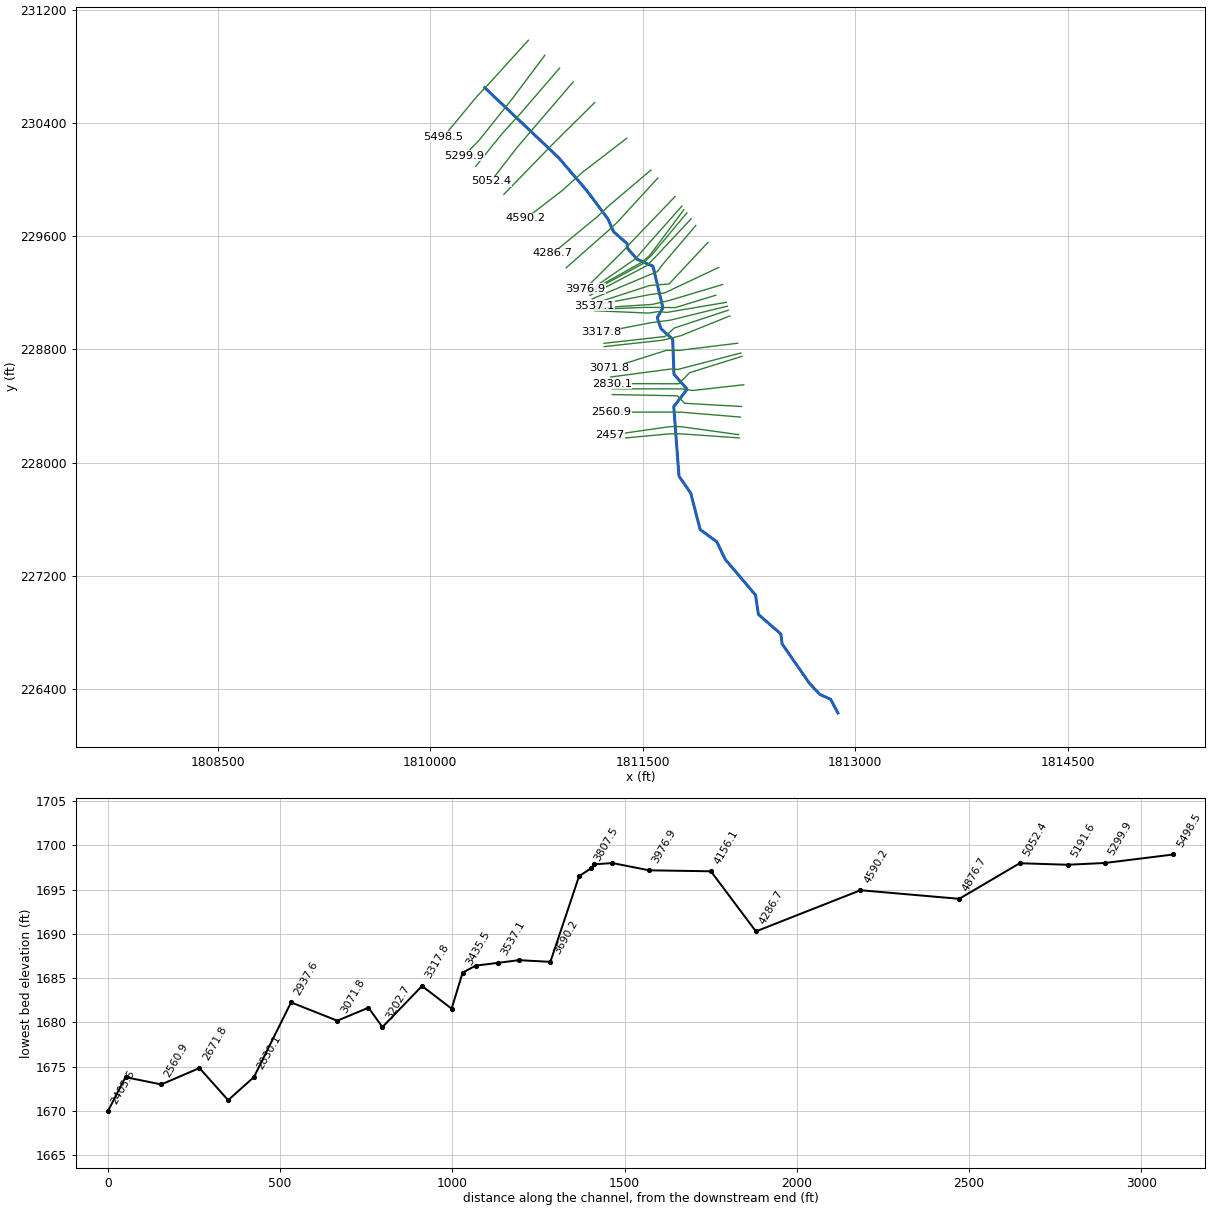
--- MarshFk1.prj (project) ---

Proj Title=MarshFk1
Current Plan=p01
Default Exp/Contr=0,0
English Units
Geom File=g01
Flow File=f01
Plan File=p01
BEGIN DESCRIPTION:
END DESCRIPTION:
DSS Export Rating Curves= 0
DSS Export Rating Curve Sorted= 0
DSS Export Volume Flow Curves= 0
DXF OffsetX= 0
DXF OffsetY= 0
DXF ScaleX= 0
DXF ScaleY= 0

--- MarshFk1.p01 (plan) ---

Plan Title=Floodplain
Program Version=4.00
Geom File=g01
Flow File=f01
K Sum by GR=0
Std Step Tol=0.01
Critical Tol=0.01
Num of Std Step Trials=20
Max Error Tol=0.3
Flow Tol Ratio=0.001
Split Flow NTrial=30
Split Flow Tol=0.02
Split Flow Ratio=0.02
Log Output Level=0
Friction Slope Method=1
Unsteady Friction Slope Method=2
Unsteady Bridges Friction Slope Method=1
Global Log Level=0
CheckData=False
Run HTab=0
Run UNet=0
Run PostProcess=0
UNET Theta=0
UNET Theta Warmup=0
UNET ZTol=0
UNET ZSATol=0
UNET MxIter=0
UNET MaxInSteps=0
UNET DtIC=0
UNET DtMin=0
UNET MaxCRTS=0
UNET WFStab=0
UNET SFStab=0
UNET WFX=0
UNET SFX=0
UNET DSS MLevel=0
UNET DZMax Abort=0
UNET Convert EG Bridges=0
UNET Use Existing IB Tables=0
UNET Froude Limit=0
UNET Froude Power=0
Write IC File=0
Echo Input=False
Echo Output=False
Write Detailed=0

--- MarshFk1.f01 (steady flow) ---

Flow Title=NFF Regression Equation
Program Version=4.00
Number of Profiles=1
Profile Names=P100yr
River Rch & RM=MarshFk1,Main      ,5498.5
558.2246
River Rch & RM=MarshFk1,Main      ,4156.1
601.9006
River Rch & RM=MarshFk1,Main      ,3537.1
660.3452
River Rch & RM=MarshFk1,Main      ,2937.6
708.8127
River Rch & RM=MarshFk1,Main      ,212.7
760.4693
Boundary for River Rch & Prof#=MarshFk1,Main      ,1
Up Type=0
Dn Type=3
Dn Slope=0.057915

--- MarshFk1.g01 (geometry) ---

Geom Title=USGS 10m DEM
Program Version=4.00

River Reach=MarshFk1        ,Main
Reach XY= 30
     1810385.352      230648.164     1810906.579      230154.122
      1811106.81      229919.386     1811255.354      229720.287
     1811293.905      229631.031     1811390.105      229546.644
     1811393.481      229512.889     1811459.303      229436.941
     1811572.246       229387.22     1811642.676      229093.369
     1811603.466      229025.405     1811610.785      228997.174
     1811629.083      228945.417     1811711.685       228871.18
     1811720.573      228623.898      1811813.63      228518.293
     1811719.213      228395.632     1811756.018      227904.519
     1811838.725       227784.81     1811905.642      227527.072
     1812023.005      227440.354     1812082.076      227317.149
     1812296.418      227063.989     1812316.671      226927.283
     1812475.317      226788.889     1812483.756      226719.692
     1812675.721       226442.27     1812750.481      226362.283
     1812826.366      226328.138     1812877.632      226231.241

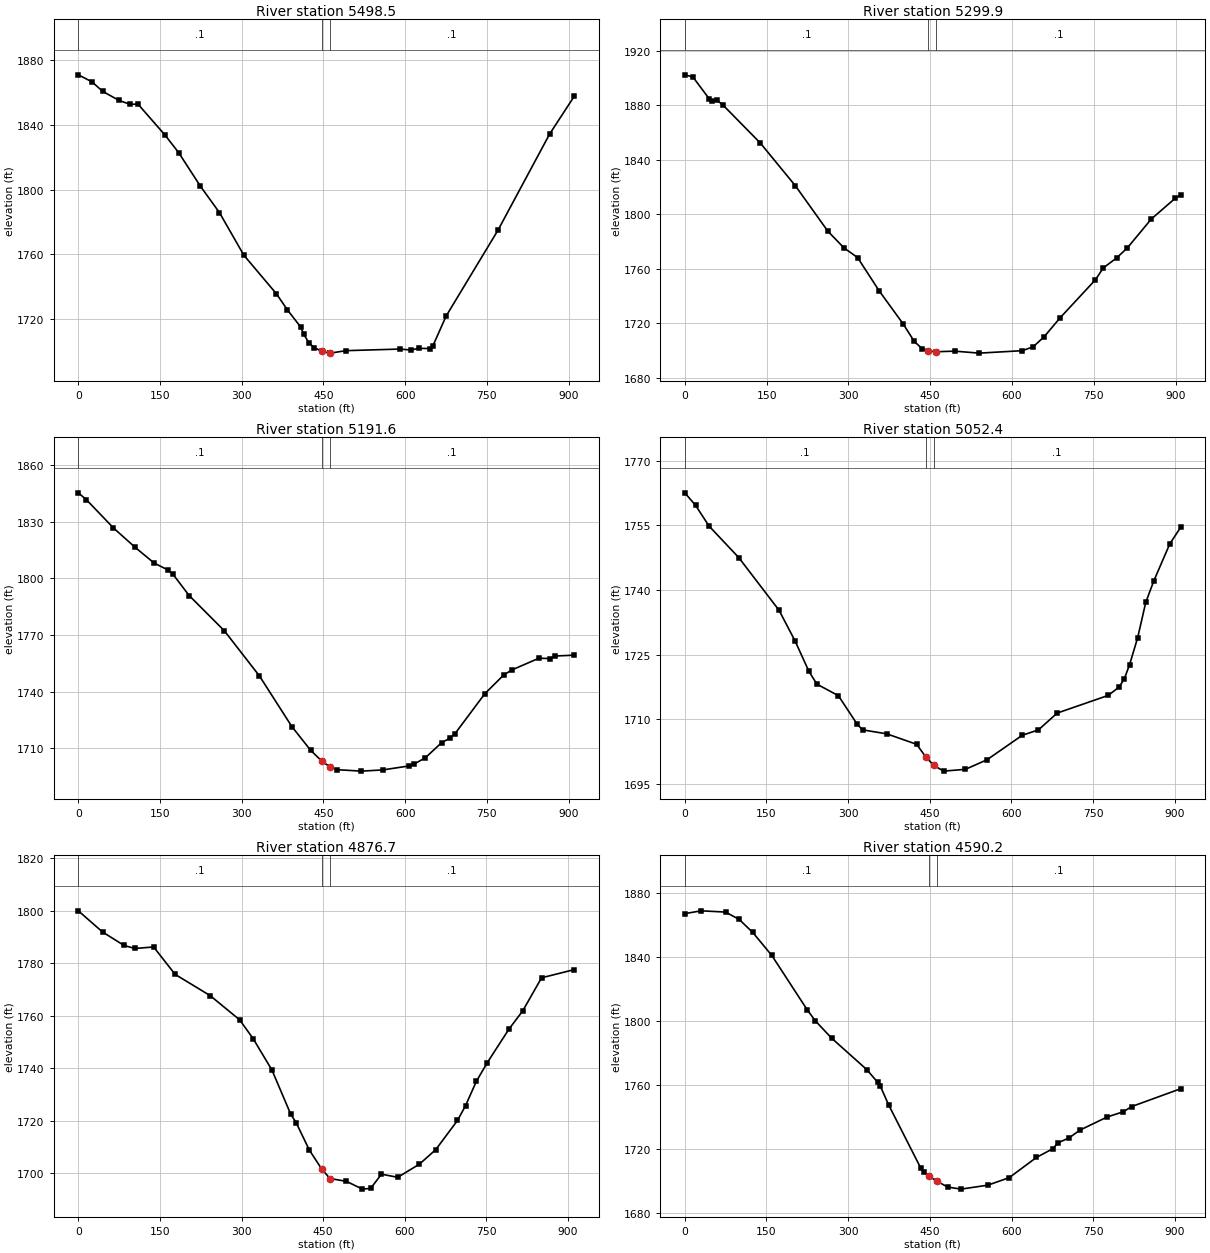
Type RM Length L Ch R = 1 ,5498.5  ,196.6,198.6,200.6
XS GIS Cut Line= 4
     1810693.045      230983.499     1810412.033      230673.422
     1810331.444      230588.652     1810092.688      230299.634
#Sta/Elev= 30
       0    1871    24.9  1866.7    44.8 1860.76    74.7 1855.17    94.6 1852.82
   109.6 1852.86   159.4 1833.67   184.3 1822.85   224.2 1802.12     259 1785.87
   303.9 1759.49   363.7 1735.65   383.6 1725.83   408.5    1715   413.5 1710.87
   423.3 1705.32   433.1 1702.35   447.6 1700.05   462.3 1698.98   462.6 1698.99
   491.6 1700.51   590.4 1701.49   610.4 1700.92   625.4 1701.94   645.4  1701.8
   650.4  1703.1   675.4 1721.98   770.4 1774.94   865.3 1834.43   910.3 1857.66
#Mann= 3 , 0 , 0
       0      .1       0   447.6    .045       0   462.6      .1       0
Bank Sta=447.6,462.6
XS Rating Curve= 0 ,0
Exp/Cntr=0.3,0.1

Type RM Length L Ch R = 1 ,5299.9  ,109.7,108.3,106.8
XS GIS Cut Line= 4
     1810809.171      230877.261     1810580.901      230572.101
     1810349.027      230281.357       1810240.9      230168.424
#Sta/Elev= 30
       0 1902.24    14.8  1900.7    44.5 1884.79    49.5 1883.14    59.4 1883.44
    69.3 1880.36   138.6 1852.14   202.9 1820.77   262.3 1787.52     292 1775.21
   316.8 1768.17   356.3 1743.81   400.9  1719.2   420.8 1706.63   435.6 1701.11
   445.5  1699.7   460.5 1699.04   495.1 1699.47   539.8 1698.02   619.1 1699.82
   638.9  1702.7   658.8 1709.93   688.5 1724.03     753 1751.81   767.6 1760.59
   792.1 1767.91   811.6 1775.24   855.6 1796.45   899.6 1811.72   909.3 1814.07
#Mann= 3 , 0 , 0
       0      .1       0   445.5    .045       0   460.5      .1       0
Bank Sta=445.5,460.5
XS Rating Curve= 0 ,0
Exp/Cntr=0.3,0.1

Type RM Length L Ch R = 1 ,5191.6  ,138.5,139.2,140
XS GIS Cut Line= 4
     1810912.656      230785.845     1810643.998      230473.688
     1810509.192      230325.603      1810322.12       230093.47
#Sta/Elev= 30
       0 1845.41    14.9 1841.73    64.5 1826.77   104.2 1816.52   138.9 1808.22
   163.8 1804.59   173.7 1802.23   203.4 1790.95     268 1772.27   332.5 1748.28
     392 1721.44   426.5 1708.85   447.5 1702.97   462.5 1699.98   475.3 1698.58
   519.3 1697.82   558.4 1698.44   607.2 1700.57   617.1 1701.69     637 1704.88
   666.8 1712.91   681.7 1715.22   691.6 1717.75   746.3  1738.9     781 1748.84
     796  1751.5   845.6  1757.7   865.5 1757.52   875.4 1758.87   910.2 1759.32
#Mann= 3 , 0 , 0
       0      .1       0   447.5    .045       0   462.5      .1       0
Bank Sta=447.5,462.5
XS Rating Curve= 0 ,0
Exp/Cntr=0.3,0.1

Type RM Length L Ch R = 1 ,5052.4  ,177.2,175.7,174.2
XS GIS Cut Line= 4
     1811009.808       230689.84     1810758.711      230396.694
      1810613.34      230226.092     1810429.523      229988.211
#Sta/Elev= 30
       0 1762.58    19.8 1759.67    44.5 1754.87      99 1747.57   173.2 1735.31
   202.9 1728.11   227.6 1721.25   242.5 1718.19   282.1  1715.5   316.7 1708.87
   326.6 1707.57   371.1 1706.64   425.8 1704.22   442.5 1701.32   457.5  1699.3
   475.6 1697.99   515.5 1698.41   555.3 1700.64     620 1706.32   649.6 1707.56
     684 1711.46   777.7 1715.56   797.4 1717.46   807.2 1719.35   817.1 1722.73
   831.9 1728.96   846.7 1737.13   861.5 1742.13     891 1750.76   910.8 1754.56
#Mann= 3 , 0 , 0
       0      .1       0   442.5    .045       0   457.5      .1       0
Bank Sta=442.5,457.5
XS Rating Curve= 0 ,0
Exp/Cntr=0.3,0.1

Type RM Length L Ch R = 1 ,4876.7  ,287.9,286.5,285.1
XS GIS Cut Line= 4
     1811160.898      230543.003     1810883.453      230268.348
     1810798.302       230181.17     1810520.316      229895.109
#Sta/Elev= 30
       0 1800.05    44.5 1791.98      84 1786.85   103.8  1785.7   138.4 1786.27
   177.9 1775.82   242.2 1767.74   296.5 1758.49   321.2 1751.35   355.8 1739.36
   390.4  1722.5   400.2 1719.34   424.5 1708.88   447.5 1701.56   462.5 1698.02
   492.8 1696.92   522.2 1693.97   537.2 1694.26   557.1 1699.66     587 1698.48
   626.9  1703.5   656.9 1709.04   696.8 1720.14   711.7 1725.84   731.6  1735.1
   751.6 1742.19   791.5 1755.01   816.4 1761.82   851.3 1774.52   911.2 1777.63
#Mann= 3 , 0 , 0
       0      .1       0   447.5    .045       0   462.5      .1       0
Bank Sta=447.5,462.5
XS Rating Curve= 0 ,0
Exp/Cntr=0.3,0.1

Type RM Length L Ch R = 1 ,4590.2  ,303,303.5,304.1
XS GIS Cut Line= 4
     1811387.406      230291.334     1811071.151      230047.536
     1810932.943      229922.424     1810675.499       229724.36
#Sta/Elev= 30
       0 1867.02      30 1868.77    74.9    1868    99.8 1863.42   124.8 1855.27
   159.7 1840.95   224.6 1807.06   239.6 1800.11   269.5 1789.27   334.4 1769.54
   354.4 1761.58   359.4 1759.05   374.4 1747.52   433.7 1707.84   438.6 1705.55
   447.8 1703.14   462.8 1699.92   482.7 1696.26   507.2 1694.94   556.3  1697.4
   595.7 1702.09   645.7  1714.7   675.7 1720.16   685.7 1723.91   705.7 1726.94
   725.7  1731.8   775.6 1739.98   805.6  1743.3   820.6  1746.5   910.6 1757.64
#Mann= 3 , 0 , 0
       0      .1       0   447.8    .045       0   462.8      .1       0
Bank Sta=447.8,462.8
XS Rating Curve= 0 ,0
Exp/Cntr=0.3,0.1

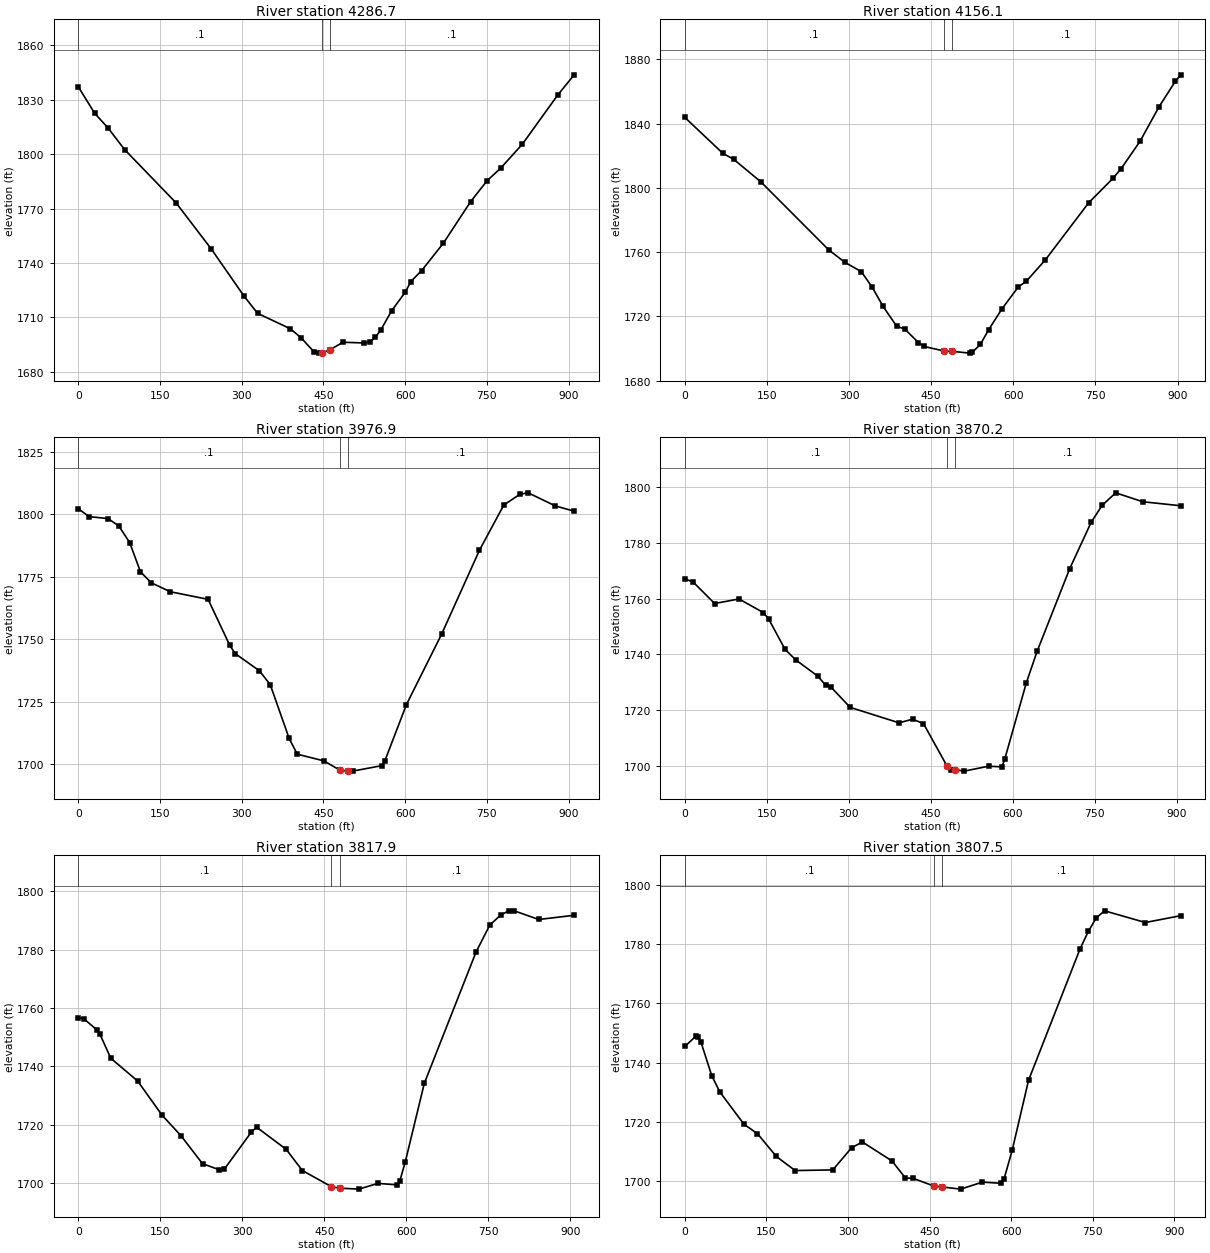
Type RM Length L Ch R = 1 ,4286.7  ,130.8,130.6,130.4
XS GIS Cut Line= 4
     1811558.242      230066.581     1811261.587      229814.875
     1811180.968      229738.189     1810864.358      229477.833
#Sta/Elev= 30
       0 1837.18    29.9 1822.63    54.9 1814.35    84.8 1802.61   179.6 1773.13
   244.4 1747.59   304.3 1721.68   329.2 1712.22     389 1703.76   408.4  1698.9
   432.6 1691.02   442.3 1690.29   447.6 1690.43   462.6 1692.27   485.8 1696.29
   525.3 1695.89   535.3 1696.53   545.3 1698.95   555.3  1703.1   575.3 1713.74
   600.3 1723.95   610.3 1729.77   630.3 1735.84   670.3 1751.02   720.3 1773.92
   750.3 1785.37   775.3 1792.32   815.2 1805.58   880.2 1832.72   910.2  1843.8
#Mann= 3 , 0 , 0
       0      .1       0   447.6    .045       0   462.6      .1       0
Bank Sta=447.6,462.6
XS Rating Curve= 0 ,0
Exp/Cntr=0.3,0.1

Type RM Length L Ch R = 1 ,4156.1  ,174.5,179.2,183.8
XS GIS Cut Line= 4
     1811606.371      230009.635     1811318.132      229694.954
     1811260.571      229641.418     1810960.424      229376.672
#Sta/Elev= 30
       0 1843.87    69.5 1821.49    89.3 1817.77   138.9 1803.74     263 1761.33
   292.8 1753.53   322.5 1747.79   342.4 1738.05   362.2 1726.17     387 1713.81
   401.9 1712.04   426.7 1703.66   436.6 1701.27   472.7 1698.46   487.7 1698.23
   520.2 1697.08   525.1  1697.7   539.9 1702.47   554.8  1711.6   579.5 1724.72
   609.1  1738.3   623.9 1741.88   658.5 1755.13   737.6 1790.68     782 1805.92
   796.9 1811.93   831.5    1829     866  1850.4   895.7 1866.23   905.6 1870.38
#Mann= 3 , 0 , 0
       0      .1       0   472.7    .045       0   487.7      .1       0
Bank Sta=472.7,487.7
XS Rating Curve= 0 ,0
Exp/Cntr=0.3,0.1

Type RM Length L Ch R = 1 ,3976.9  ,108.4,106.7,99.7
XS GIS Cut Line= 4
     1811728.387      229879.416     1811436.474      229575.001
     1811367.643      229500.936     1811093.578      229227.373
#Sta/Elev= 30
       0 1802.28    19.8 1799.13    54.6 1798.34    74.4 1795.37    94.3  1788.7
   114.1 1777.02     134 1772.61   168.7 1769.05   238.2 1765.99   277.9  1747.6
   287.8 1744.28   332.4 1737.38   352.3  1731.8     387 1710.26   401.9 1703.97
   450.6  1701.3   479.5 1697.67   479.5 1697.66   494.5 1697.21   503.6 1697.19
   557.6 1699.41   562.6 1701.29   602.3 1723.87   666.8 1752.04   736.3 1785.68
     781 1803.79   810.8 1808.12   825.7 1808.66   875.4 1803.43   910.1  1801.3
#Mann= 3 , 0 , 0
       0      .1       0   479.5    .045       0   494.5      .1       0
Bank Sta=479.5,494.5
XS Rating Curve= 0 ,0
Exp/Cntr=0.3,0.1

Type RM Length L Ch R = 1 ,3870.2  ,56.1,52.3,47.6
XS GIS Cut Line= 4
     1811776.174      229811.454     1811522.675      229525.516
     1811452.288      229441.811     1811109.996      229205.319
#Sta/Elev= 30
       0 1767.02    14.9    1766    54.6  1758.2    99.2 1759.84   143.9 1754.94
   153.8 1752.54   183.6  1741.7   203.5 1737.89   243.2 1732.15   258.1 1728.81
     268  1728.1   302.7  1720.9   392.1 1715.36   416.9 1716.66   436.8 1715.09
   480.3 1699.71   486.5 1698.53   495.3 1698.51   511.3 1698.01   555.9 1699.77
   580.6 1699.55   585.6 1702.32   625.2  1729.8     645 1741.13   704.5 1770.73
   744.1  1787.5   763.9 1793.48   788.7 1797.96   838.2 1794.76   907.5 1793.32
#Mann= 3 , 0 , 0
       0      .1       0   480.3    .045       0   495.3      .1       0
Bank Sta=480.3,495.3
XS Rating Curve= 0 ,0
Exp/Cntr=0.3,0.1

Type RM Length L Ch R = 1 ,3817.9  ,9.8,10.4,15
XS GIS Cut Line= 4
     1811789.735      229785.272     1811550.409      229464.665
     1811499.834      229418.606     1811116.912      229204.566
#Sta/Elev= 30
       0 1756.69     9.9 1756.32    34.6 1752.41    39.5 1751.03    59.3  1742.8
   108.7 1734.92   153.1 1723.26   187.7 1716.22   227.2  1706.6   256.8 1704.59
   266.7 1704.62   316.1 1717.31     326 1719.14   380.3 1711.52   409.8 1704.26
   463.1  1698.7   478.1 1698.21   513.4 1697.87   548.2 1699.84   583.1 1699.33
   588.1 1700.61   598.1 1707.15     633 1734.14   727.7 1779.22   752.6 1788.39
   772.6  1791.9   787.5 1793.35   797.5 1793.35   842.4 1790.38   907.2 1791.82
#Mann= 3 , 0 , 0
       0      .1       0   463.1    .045       0   478.1      .1       0
Bank Sta=463.1,478.1
XS Rating Curve= 0 ,0
Exp/Cntr=0.3,0.1

Type RM Length L Ch R = 1 ,3807.5  ,33.8,34.1,32.6
XS GIS Cut Line= 4
     1811811.625      229763.979      1811558.44      229459.879
     1811494.841      229401.512     1811117.449      229196.909
#Sta/Elev= 30
       0 1745.48    19.8 1748.86    24.7 1748.61    29.7 1746.97    49.5 1735.65
    64.3 1730.18   108.8 1719.26   133.6 1716.08   168.2 1708.41   202.8 1703.66
     272 1703.88   306.7 1711.36   326.4 1713.28   380.9 1706.89   405.3 1701.18
   419.7 1701.03   457.6 1698.45   472.6 1698.14     507  1697.4   546.9 1699.76
   581.9 1699.36   586.8 1700.86   601.8 1710.53   631.8  1734.1   726.6 1778.43
   741.6 1784.25   756.6 1788.89   771.5  1791.2   846.4 1787.26   911.3 1789.56
#Mann= 3 , 0 , 0
       0      .1       0   457.6    .045       0   472.6      .1       0
Bank Sta=457.6,472.6
XS Rating Curve= 0 ,0
Exp/Cntr=0.3,0.1

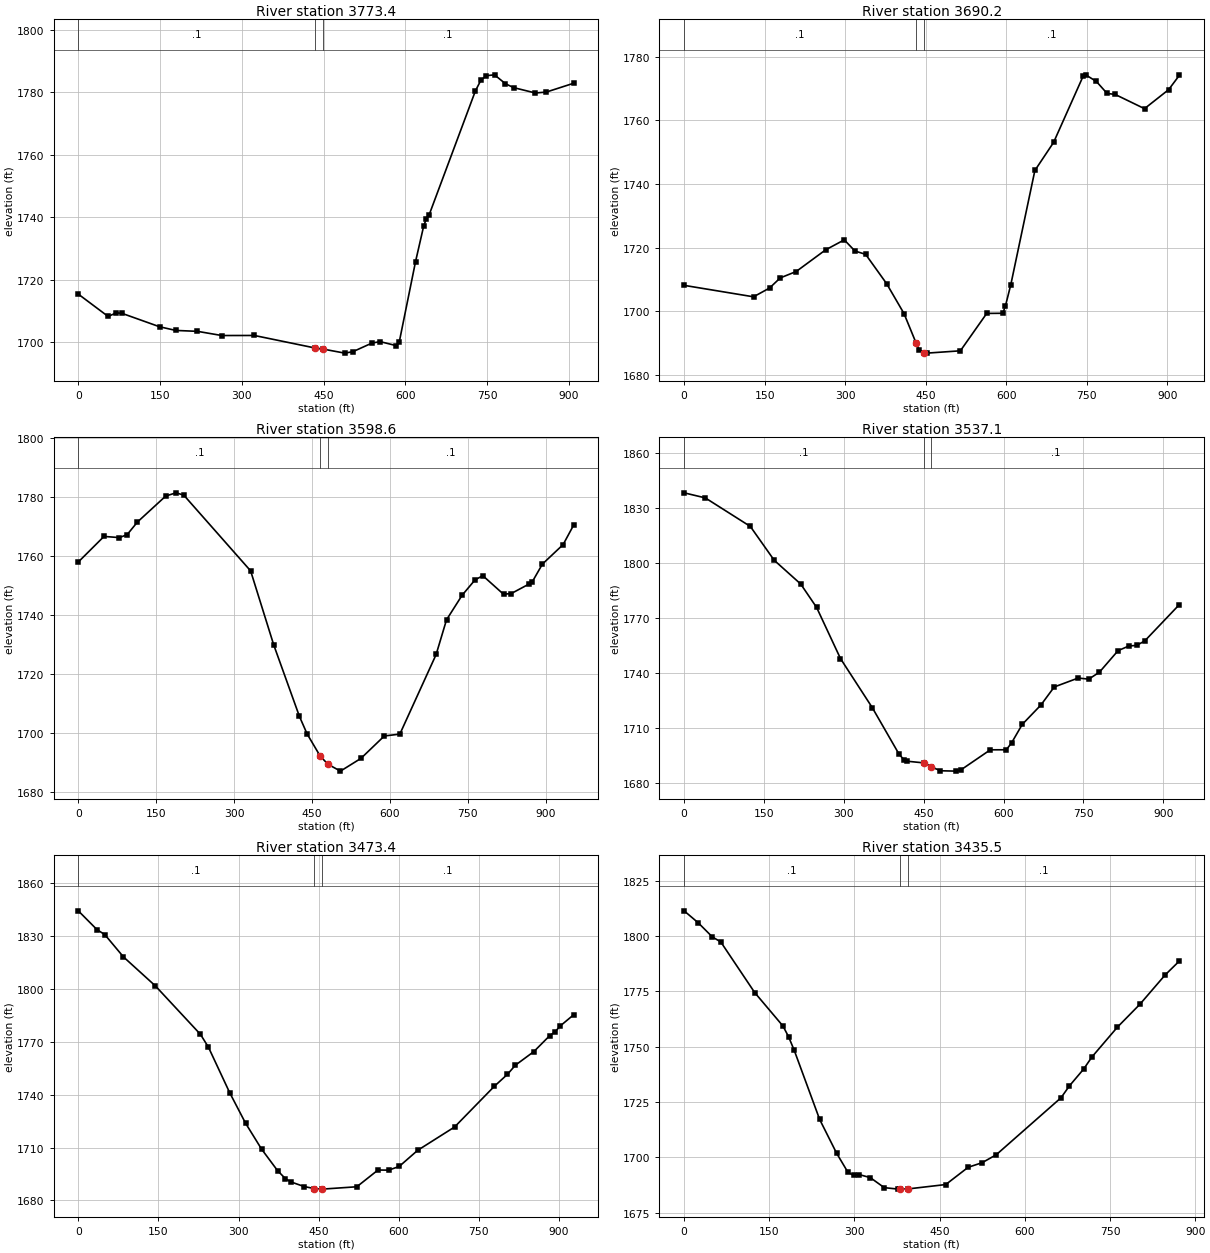
Type RM Length L Ch R = 1 ,3773.4  ,87.9,83.2,78.6
XS GIS Cut Line= 4
     1811842.581      229722.849     1811577.761      229439.752
     1811526.983      229389.681     1811128.262      229181.535
#Sta/Elev= 30
       0  1715.4    54.7 1708.26    69.6 1709.39    79.5 1709.29   149.1 1704.96
   178.9 1703.78   218.7 1703.49   263.4 1702.15     323 1702.17     434 1698.18
     449 1697.82     489 1696.52   503.9 1696.98   538.9 1699.74   553.9  1700.2
   583.9  1698.9   588.9 1699.99   618.9 1725.81   633.9 1737.23   638.9 1739.57
   643.9 1740.78   728.8 1780.44   738.8 1783.83   748.8 1785.29   763.8 1785.56
   783.8 1782.72   798.8 1781.47   838.8 1779.75   858.8 1780.04   908.8 1782.85
#Mann= 3 , 0 , 0
       0      .1       0     434    .045       0     449      .1       0
Bank Sta=434,449
XS Rating Curve= 0 ,0
Exp/Cntr=0.3,0.1

Type RM Length L Ch R = 1 ,3690.2  ,102.6,91.7,84.6
XS GIS Cut Line= 5
     1811874.794      229675.268     1811636.812      229394.637
     1811604.374      229349.583     1811502.554      229307.233
     1811144.409      229156.618
#Sta/Elev= 30
       0 1708.14   129.3 1704.54   159.1 1707.29     179 1710.47   208.8 1712.49
   263.5 1719.28   298.3 1722.43   318.2 1718.93   338.1 1717.88   377.2 1708.67
   409.6 1699.27   432.4 1689.89   437.8  1687.8   447.4    1687   452.2 1686.85
   514.6 1687.58   563.6 1699.32   593.5 1699.37   598.5 1701.68   608.5 1708.38
   653.3 1744.22   688.2 1753.05     743 1773.78   747.9 1774.27   767.9 1772.18
   787.8 1768.42   802.7 1768.12   857.5 1763.64   902.4 1769.61   922.3 1774.09
#Mann= 3 , 0 , 0
       0      .1       0   432.4    .045       0   447.4      .1       0
Bank Sta=432.4,447.4
XS Rating Curve= 0 ,0
Exp/Cntr=0.3,0.1

Type RM Length L Ch R = 1 ,3598.6  ,60.8,61.5,62.1
XS GIS Cut Line= 4
     1811960.095      229554.926     1811686.171       229261.78
     1811548.408      229250.566     1811154.342      229122.415
#Sta/Elev= 30
       0 1757.89    49.5 1766.56    79.2 1766.16    94.1 1767.17   113.9 1771.44
   168.4 1780.24   188.2 1781.33   203.1 1780.56   331.9 1754.89   376.4  1729.8
   425.9 1705.58   440.7 1699.64   465.9 1692.13   480.9 1689.36   504.9 1687.04
   544.4 1691.36   589.4 1698.95   619.3 1699.58   689.2 1726.56   709.2 1738.31
   739.1  1746.6   764.1 1751.83   779.1 1753.26     819 1746.97     834 1747.22
   868.9  1750.5   873.9 1751.04   893.9 1757.19   933.8  1763.8   953.8 1770.32
#Mann= 3 , 0 , 0
       0      .1       0   465.9    .045       0   480.9      .1       0
Bank Sta=465.9,480.9
XS Rating Curve= 0 ,0
Exp/Cntr=0.3,0.1

Type RM Length L Ch R = 1 ,3537.1  ,61.2,63.7,66.3
XS GIS Cut Line= 4
     1812036.985      229378.718     1811654.185      229198.527
     1811552.747      229187.405     1811155.546      229109.145
#Sta/Elev= 30
       0 1838.42    39.8 1835.66   124.4  1820.1   169.2 1801.67     219 1788.71
   248.9 1775.93   293.7 1748.08   353.4 1721.34   403.2 1696.22   413.1 1692.76
   418.1 1692.15   449.6 1691.24   464.6 1689.03   481.4 1686.93   510.6 1686.73
   520.3 1687.49   575.1 1698.35   605.1 1698.37   615.1 1702.18   635.1 1712.22
   670.1 1722.77   695.1  1732.6     740 1737.46     760 1736.88     780 1740.67
     815  1752.4     835  1754.9     850 1755.29     865 1757.67     930 1777.47
#Mann= 3 , 0 , 0
       0      .1       0   449.6    .045       0   464.6      .1       0
Bank Sta=449.6,464.6
XS Rating Curve= 0 ,0
Exp/Cntr=0.3,0.1

Type RM Length L Ch R = 1 ,3473.4  ,43.1,37.8,32.5
XS GIS Cut Line= 4
     1812064.021       229258.04     1811682.996      229143.809
     1811567.279      229117.436      1811157.56      229090.816
#Sta/Elev= 30
       0 1844.35    34.8 1833.73    49.7 1830.83    84.5 1818.21   144.2 1801.77
   228.7 1774.23   243.6 1766.96   283.4 1741.13   313.2 1723.78   343.1 1709.11
   372.9 1696.96   387.8 1692.33   397.8 1690.54   422.5  1687.9   441.5 1686.76
   456.5 1686.42   521.4 1687.76     561 1697.26   580.8 1697.19   600.6 1699.27
   635.2 1708.42   704.4 1721.69   778.6 1744.72   803.4 1751.59   818.2 1756.75
   852.8 1764.48   882.5 1773.52   892.4 1775.65   902.3 1779.06     927 1785.29
#Mann= 3 , 0 , 0
       0      .1       0   441.5    .045       0   456.5      .1       0
Bank Sta=441.5,456.5
XS Rating Curve= 0 ,0
Exp/Cntr=0.3,0.1

Type RM Length L Ch R = 1 ,3435.5  ,34,32,30.7
XS GIS Cut Line= 4
      1812016.44      229182.524     1811731.112      229095.178
     1811514.533      229096.446     1811157.707      229081.919
#Sta/Elev= 30
       0 1811.32    24.9 1805.91    49.7 1799.55    64.6 1797.27   124.3 1774.42
   174.1  1759.3     184 1754.45     194 1748.29   238.7 1717.12   268.6 1701.84
   288.4 1693.29   298.4 1691.82   308.2 1692.21   327.9 1690.83   352.5  1686.3
   377.2 1685.63   379.9 1685.63   394.9 1685.74   460.8  1687.7   500.2 1695.49
   524.9 1697.57   549.7 1701.15   663.8  1726.9   678.7  1732.3   703.5 1739.81
   718.3 1745.34     763 1758.76   802.7 1769.12   847.3  1782.4   872.1 1788.63
#Mann= 3 , 0 , 0
       0      .1       0   379.9    .045       0   394.9      .1       0
Bank Sta=379.9,394.9
XS Rating Curve= 0 ,0
Exp/Cntr=0.3,0.1

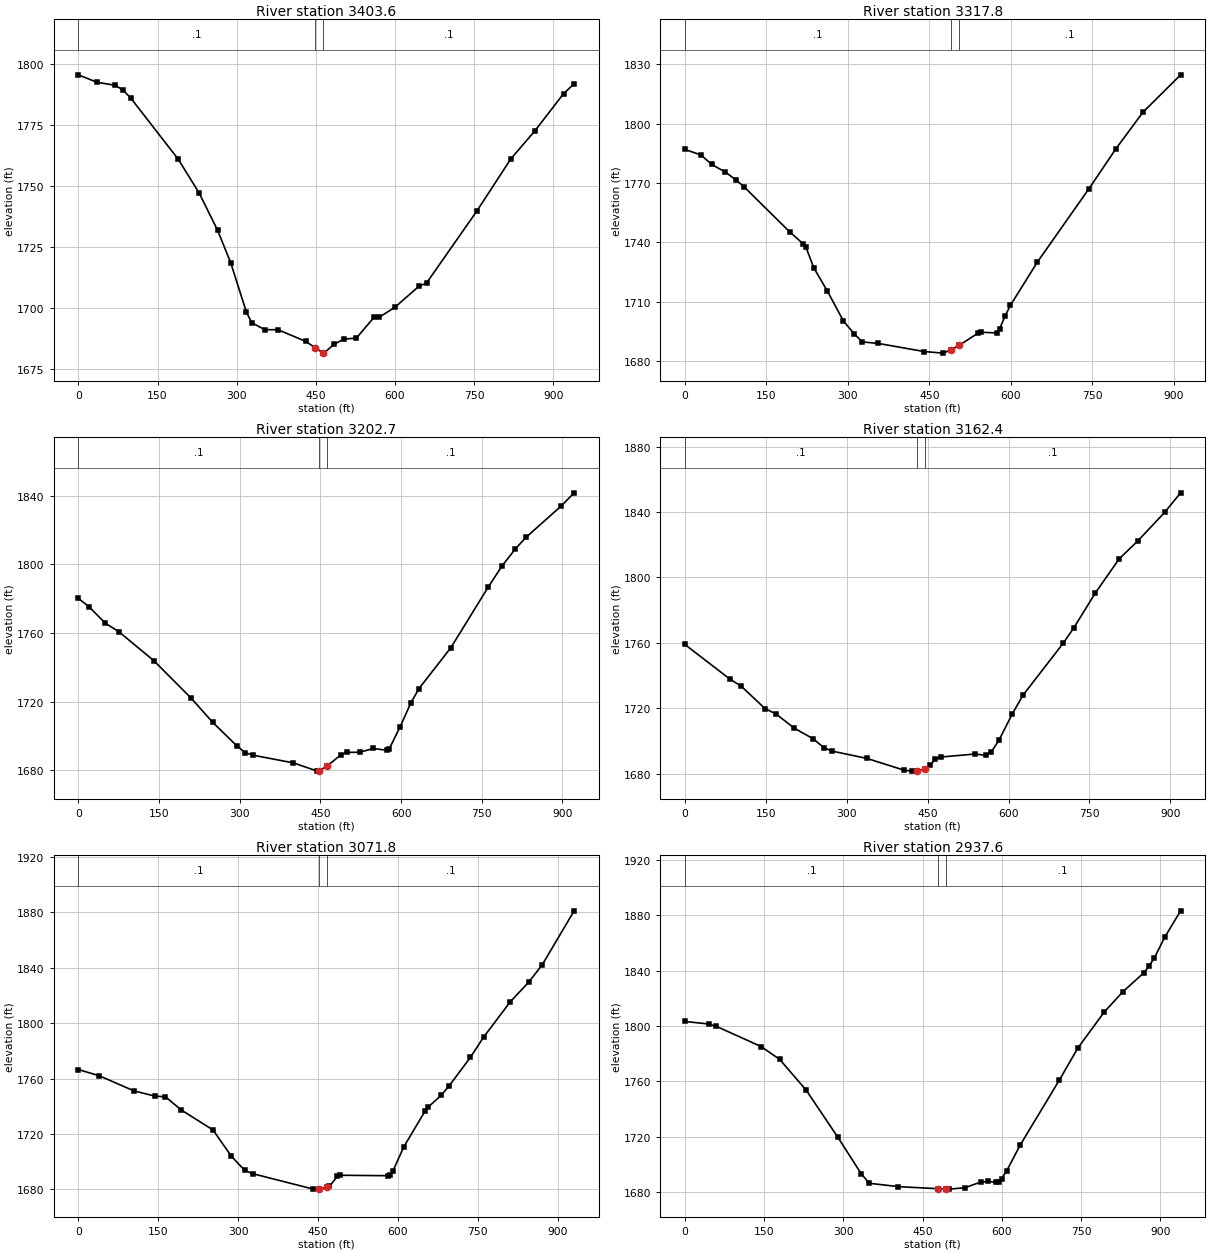
Type RM Length L Ch R = 1 ,3403.6  ,78.8,85.8,91.2
XS GIS Cut Line= 6
     1812089.849      229132.094     1811712.147      229067.944
     1811669.941      229060.975     1811611.537      229066.673
     1811541.912      229056.245     1811157.956      229072.778
#Sta/Elev= 30
       0 1795.59    34.8 1792.57    69.7  1791.3    84.6 1789.37    99.5 1786.01
   189.1 1761.06   228.9 1747.15   263.7 1731.95   288.6 1718.65   318.4 1698.35
   328.4 1694.04   353.3 1691.16   378.1 1691.15   430.8 1686.38   448.8 1683.77
   463.8 1681.62     465 1681.56   484.6  1685.2   503.3 1687.29   526.8 1687.73
     560 1696.18     570 1696.26   599.9 1700.38   644.8 1708.87   659.8 1710.33
   754.6 1739.66   819.5  1761.2   864.4  1772.5   919.3 1787.88   939.3 1791.95
#Mann= 3 , 0 , 0
       0      .1       0   448.8    .045       0   463.8      .1       0
Bank Sta=448.8,463.8
XS Rating Curve= 0 ,0
Exp/Cntr=0.3,0.1

Type RM Length L Ch R = 1 ,3317.8  ,100.8,115,129.3
XS GIS Cut Line= 4
     1812097.019      229104.763     1811693.162      229005.812
     1811555.438      228987.725     1811204.162      228919.518
#Sta/Elev= 30
       0 1786.94    29.7  1784.2    49.5 1779.37    74.2 1775.59      94 1771.62
   108.9 1768.12     193 1745.36   217.8 1739.32   222.8  1737.7   237.6 1727.12
   262.4 1715.43     292 1700.32   311.8 1693.84   326.7 1689.78   356.4    1689
   440.6 1684.92   475.3 1684.12   490.6  1685.8   505.6 1688.16   539.8 1694.23
   544.8 1694.66   574.6 1694.32   579.6 1696.46   589.5 1702.94   599.4 1708.29
   649.1 1730.16   743.6 1767.01   793.3 1787.19     843 1805.66   912.6 1824.62
#Mann= 3 , 0 , 0
       0      .1       0   490.6    .045       0   505.6      .1       0
Bank Sta=490.6,505.6
XS Rating Curve= 0 ,0
Exp/Cntr=0.3,0.1

Type RM Length L Ch R = 1 ,3202.7  ,51.9,40.4,28.9
XS GIS Cut Line= 4
     1812102.772      229075.998     1811723.077      228950.584
     1811657.494      228890.753     1811227.174      228842.429
#Sta/Elev= 30
       0 1780.14      20 1775.17      50 1765.68      75 1760.75     140 1743.91
   209.9 1721.93   249.9 1707.85   294.9 1694.15   309.9 1690.27   324.9 1688.75
   399.9 1684.27   444.3 1679.48   446.7 1679.55   461.7 1682.28   488.6  1689.1
   498.6 1690.41   523.5 1690.48   548.4 1692.69   573.3  1691.6   578.2 1692.56
   598.2 1705.35     618 1719.08     633 1727.46   692.7 1751.45   762.4 1786.91
   787.3 1798.82   812.2 1808.83   832.1 1815.63   896.8 1833.66   921.7 1841.57
#Mann= 3 , 0 , 0
       0      .1       0   446.7    .045       0   461.7      .1       0
Bank Sta=446.7,461.7
XS Rating Curve= 0 ,0
Exp/Cntr=0.3,0.1

Type RM Length L Ch R = 1 ,3162.4  ,95.8,90.6,85.4
XS GIS Cut Line= 4
     1812114.101      229035.738     1811769.294      228896.374
     1811637.138      228863.935     1811228.655      228819.483
#Sta/Elev= 30
       0 1759.09    84.3 1737.72   104.1 1733.71   148.8 1719.83   168.6 1716.69
   203.3 1707.83     238 1701.41   257.9 1695.97   272.7 1693.92   337.2 1689.46
   405.9  1682.3   420.5 1681.67   430.1 1681.75   445.1 1683.01   454.5 1685.17
   464.2 1688.98     474 1690.26   537.7 1692.13   557.5 1691.36   567.4  1693.1
   582.2 1700.53     607  1716.7   626.8 1728.06   701.1 1759.74   720.9 1769.17
   760.5 1790.34     805 1811.35   839.7 1822.37   889.2 1839.72   918.9  1851.7
#Mann= 3 , 0 , 0
       0      .1       0   430.1    .045       0   445.1      .1       0
Bank Sta=430.1,445.1
XS Rating Curve= 0 ,0
Exp/Cntr=0.3,0.1

Type RM Length L Ch R = 1 ,3071.8  ,135.3,134.1,132.9
XS GIS Cut Line= 4
     1812170.399      228843.381     1811762.082      228793.079
     1811667.388       228792.89     1811262.537      228664.682
#Sta/Elev= 30
       0  1766.5    39.6 1761.97   104.1 1751.14   143.7 1747.32   163.6 1746.82
   193.3  1737.3   252.8 1722.89   287.5 1703.85   312.3 1693.73   327.1 1691.37
   441.3  1680.2   450.9 1680.38   465.9  1681.4   471.2 1682.15   486.2 1689.35
   491.2 1690.21     581 1689.88     586 1690.63     591 1693.61     611 1710.75
     651 1736.56     656 1739.19     681 1747.82     696 1754.65   735.9 1775.21
   760.9 1789.92   810.9 1815.39   845.8 1829.67   870.8 1842.04   930.8 1881.03
#Mann= 3 , 0 , 0
       0      .1       0   450.9    .045       0   465.9      .1       0
Bank Sta=450.9,465.9
XS Rating Curve= 0 ,0
Exp/Cntr=0.3,0.1

Type RM Length L Ch R = 1 ,2937.6  ,87.7,107.6,124.6
XS GIS Cut Line= 4
      1812192.94      228774.222     1811748.659      228658.335
       1811697.9      228660.959     1811273.027      228604.551
#Sta/Elev= 30
       0 1803.27    44.9 1801.47    59.9 1799.72   144.7 1785.14   179.7 1775.86
   229.6 1753.79   289.5 1719.85   334.4 1693.12   349.4  1686.5   404.2 1684.06
   478.8 1682.59   493.8 1682.31   500.7 1682.27   529.9 1683.25   559.8  1687.3
   574.8 1687.88   589.7 1687.11   594.7  1687.7   599.7 1689.89   609.6 1695.65
   634.6 1713.87   709.3 1761.14   744.2 1784.19     794 1810.08   828.9  1824.6
   868.8 1838.32   878.8 1843.28   888.7 1849.08   908.7 1864.19   938.6 1883.12
#Mann= 3 , 0 , 0
       0      .1       0   478.8    .045       0   493.8      .1       0
Bank Sta=478.8,493.8
XS Rating Curve= 0 ,0
Exp/Cntr=0.3,0.1

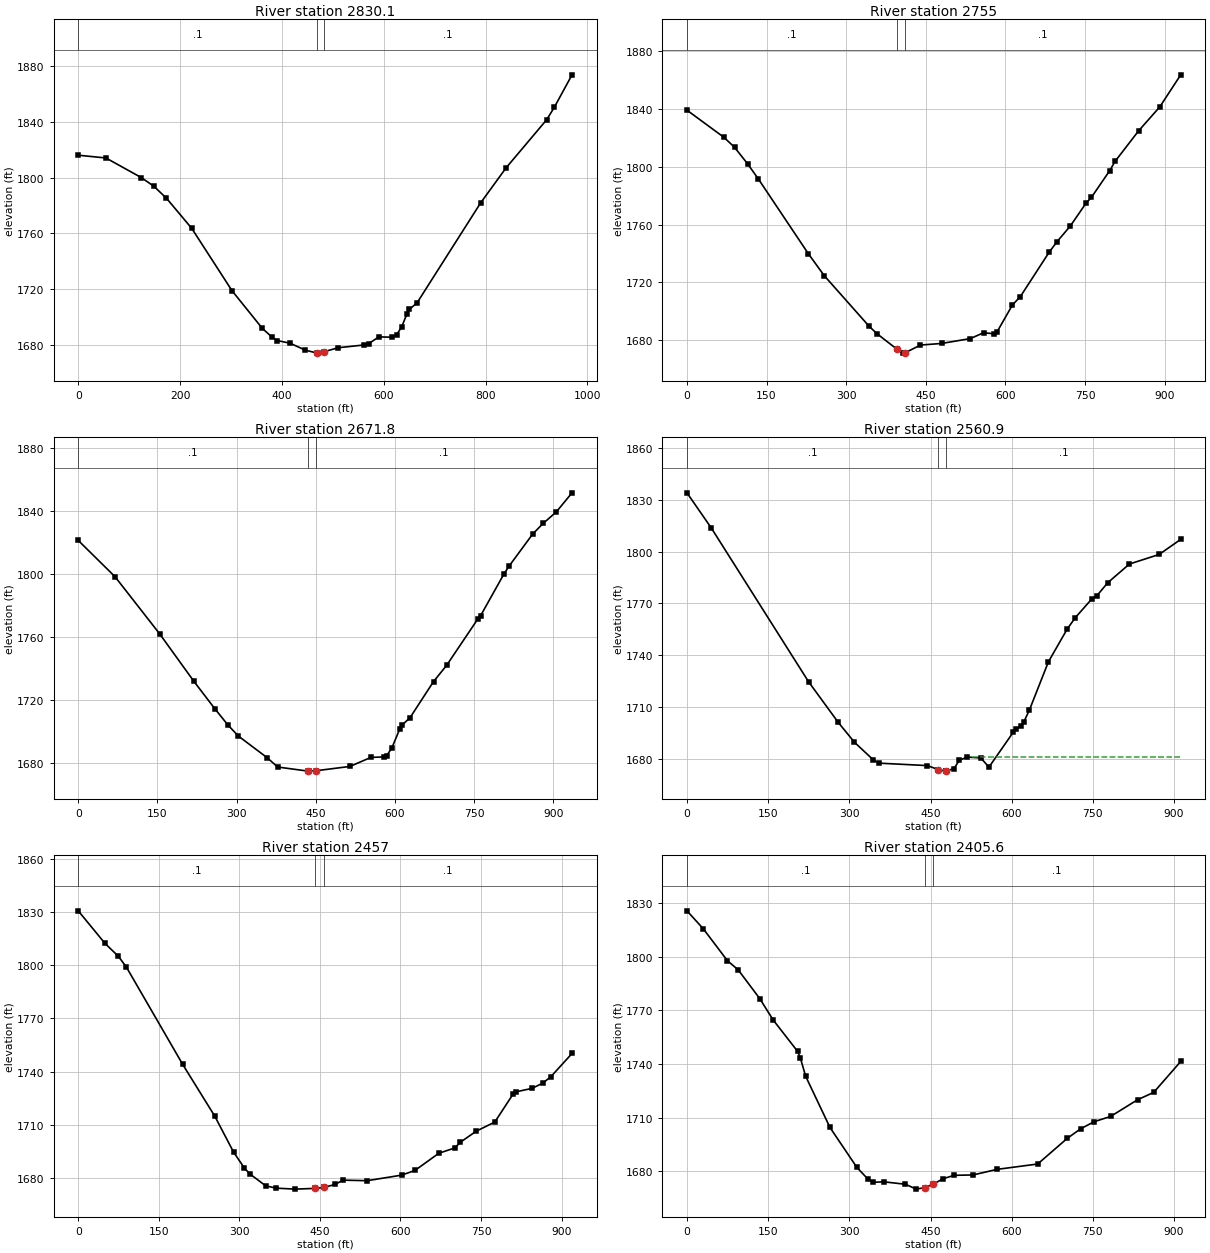
Type RM Length L Ch R = 1 ,2830.1  ,97.3,75,55.6
XS GIS Cut Line= 4
     1812200.244      228750.336     1811831.655      228635.336
       1811755.1      228556.854      1811281.14      228557.787
#Sta/Elev= 30
       0 1816.14    54.4 1814.16   123.8 1800.07   148.5 1793.83   173.3  1785.2
   222.8  1763.6     302 1718.73   361.4 1691.68   381.2 1685.11   391.1 1682.87
     416 1680.97   445.9 1675.97   468.5 1673.95   470.8 1673.84   483.5 1674.94
   510.7 1677.72   560.6 1679.68   570.6 1680.72   590.5 1685.52   615.5 1685.28
   625.5 1687.19   635.4 1692.82   645.4 1701.97   650.4 1705.35   665.4 1709.99
   790.1 1781.78     840 1806.95   919.8 1841.59   934.8 1850.49   969.7 1873.94
#Mann= 3 , 0 , 0
       0      .1       0   468.5    .045       0   483.5      .1       0
Bank Sta=468.5,483.5
XS Rating Curve= 0 ,0
Exp/Cntr=0.3,0.1

Type RM Length L Ch R = 1 ,2755    ,98.5,83.2,68
XS GIS Cut Line= 4
     1812213.475      228549.989     1811852.535      228509.248
     1811776.646       228520.55     1811286.327      228521.142
#Sta/Elev= 30
       0 1838.95    69.7 1820.19    89.6 1813.36   114.4 1801.84   134.4 1791.52
   228.9 1739.75   258.7 1724.68   343.3 1689.72   358.3 1684.55   396.1  1673.8
   406.4 1671.22   411.1 1671.48     440  1676.8   479.6 1677.89   534.1 1681.27
   558.8  1685.3   578.6 1684.58   583.6 1685.48   613.3 1704.52   628.2 1710.26
   682.6 1741.01   697.5 1748.28   722.3 1758.98     752  1774.8   761.9 1778.68
   796.6 1797.26   806.5 1803.55     851  1824.7   890.7 1841.15   930.3 1863.35
#Mann= 3 , 0 , 0
       0      .1       0   396.1    .045       0   411.1      .1       0
Bank Sta=396.1,411.1
XS Rating Curve= 0 ,0
Exp/Cntr=0.3,0.1

Type RM Length L Ch R = 1 ,2671.8  ,92.2,110.9,129.7
XS GIS Cut Line= 4
     1812197.277      228396.278     1811795.379      228418.994
     1811745.742      228471.743     1811285.742       228480.59
#Sta/Elev= 30
       0 1821.53    69.6 1798.49   154.1 1762.17   218.7 1732.09   258.4 1714.65
   283.3 1704.25   303.2 1697.17   357.8 1683.38   377.7 1677.46   435.1 1674.86
   436.3 1674.85   450.1 1675.09   514.6 1677.83   554.1 1683.56   578.9 1683.89
   583.8 1684.58   593.7 1689.41   608.5 1701.33   613.5 1704.21   628.3  1708.8
   672.9 1731.83   697.6 1742.07     757 1771.73   761.9 1773.61   806.4  1800.3
   816.3 1805.37   860.8 1825.65   880.6 1832.39   905.4 1839.66   935.1 1851.79
#Mann= 3 , 0 , 0
       0      .1       0   435.1    .045       0   450.1      .1       0
Bank Sta=435.1,450.1
XS Rating Curve= 0 ,0
Exp/Cntr=0.3,0.1

Type RM Length L Ch R = 1 ,2560.9  ,104,103.8,103.7
XS GIS Cut Line= 4
     1812189.578      228321.577      1811766.71      228356.525
     1811653.124      228357.037     1811278.821      228355.931
#Sta/Elev= 30
       0 1833.95    44.9 1813.66   224.6 1724.73   279.5 1701.17   309.5 1689.68
   344.4 1679.47   354.4 1677.62   444.1  1676.2     464 1673.94   478.6    1673
     479 1673.01   493.4 1674.51   503.3 1679.34   518.1 1681.14   542.9 1680.62
   557.9  1675.3   602.8 1695.49   607.8 1697.37   617.8 1699.07   622.7  1701.7
   632.7 1708.38   667.7 1736.17   702.6 1755.25   717.6 1761.81   747.5 1772.44
   757.5 1774.52   777.4 1781.97   817.4 1792.77   872.3  1798.3   912.2 1807.03
#Mann= 3 , 0 , 0
       0      .1       0     464    .045       0     479      .1       0
#XS Ineff= 2 , 0
                          527.02         1681.37
Permanent Ineff=
       F       F
Bank Sta=464,479
XS Rating Curve= 0 ,0
Exp/Cntr=0.3,0.1

Type RM Length L Ch R = 1 ,2457    ,50.9,51.5,52.1
XS GIS Cut Line= 4
     1812177.119      228197.442     1811767.018      228254.201
     1811692.931      228254.201     1811266.003      228193.061
#Sta/Elev= 30
       0 1830.69    49.9 1812.31    74.8 1805.04    89.8  1798.9   194.5 1744.13
   254.4 1714.86   289.3 1694.67   309.3 1685.73   319.2 1682.47   349.2 1675.65
   369.1 1674.36     404 1673.82   441.7 1674.24   456.7 1674.75   478.2 1676.44
     493 1678.89   537.7 1678.57   602.1  1681.7   626.9 1684.34   671.5 1694.05
   701.3 1697.04   711.2 1700.18   740.9 1706.45   775.6 1711.62   810.3 1727.67
   815.3 1728.68     845 1730.61   864.8 1733.55   879.7 1737.08   919.4 1750.27
#Mann= 3 , 0 , 0
       0      .1       0   441.7    .045       0   456.7      .1       0
Bank Sta=441.7,456.7
XS Rating Curve= 0 ,0
Exp/Cntr=0.3,0.1

Type RM Length L Ch R = 1 ,2405.6  ,37,37.3,37.7
XS GIS Cut Line= 4
     1812181.366      228174.312     1811758.746      228203.852
     1811683.957      228202.701     1811271.934      228163.828
#Sta/Elev= 30
       0 1825.57    29.9 1815.64    74.8 1797.68    94.7 1792.56   134.6 1776.44
   159.5 1764.45   204.4 1747.01   209.3 1743.55   219.3 1733.09   264.2 1704.44
     314 1682.07   333.9 1675.71   343.9 1673.76   363.8 1674.04   403.7 1672.67
   423.6 1669.95   439.7 1670.82   454.7 1672.69   473.5 1675.79   493.5 1677.67
   528.4 1677.87   573.2 1681.01     648 1683.99   702.9  1698.4   727.8 1703.77
   752.7 1707.69   782.7 1710.59   832.5 1719.92   862.4 1724.05   912.3 1741.33
#Mann= 3 , 0 , 0
       0      .1       0   439.7    .045       0   454.7      .1       0
Bank Sta=439.7,454.7
XS Rating Curve= 0 ,0
Exp/Cntr=0.3,0.1