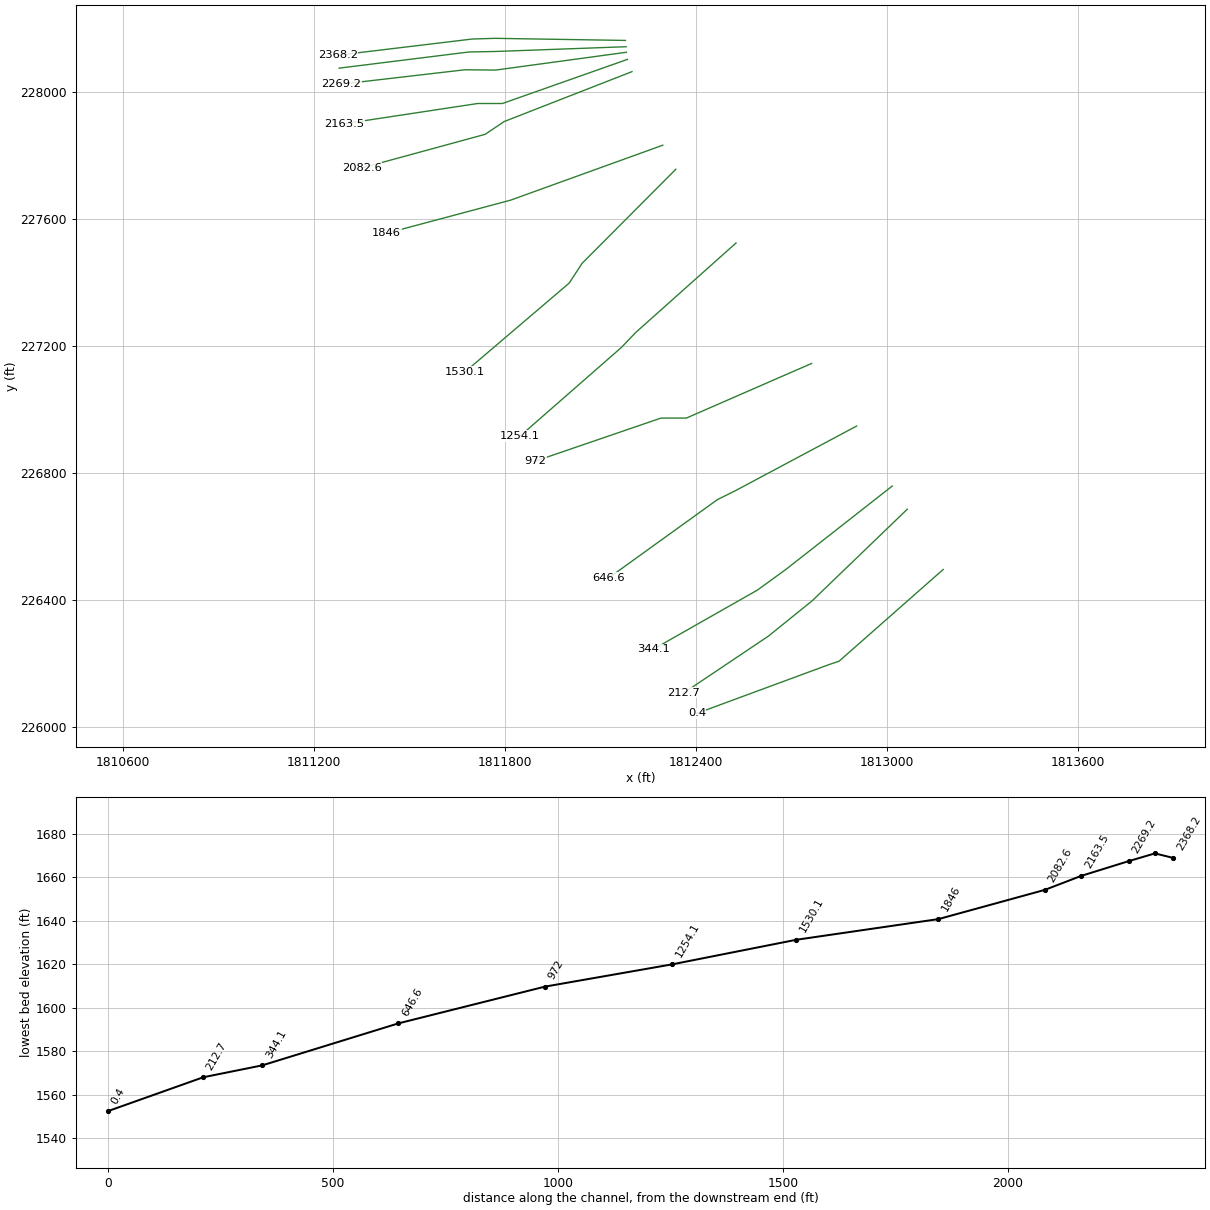
HEC-RAS study MarshFk1.prj: MarshFk1

--- MarshFk1.g01 (geometry) --- (continued)

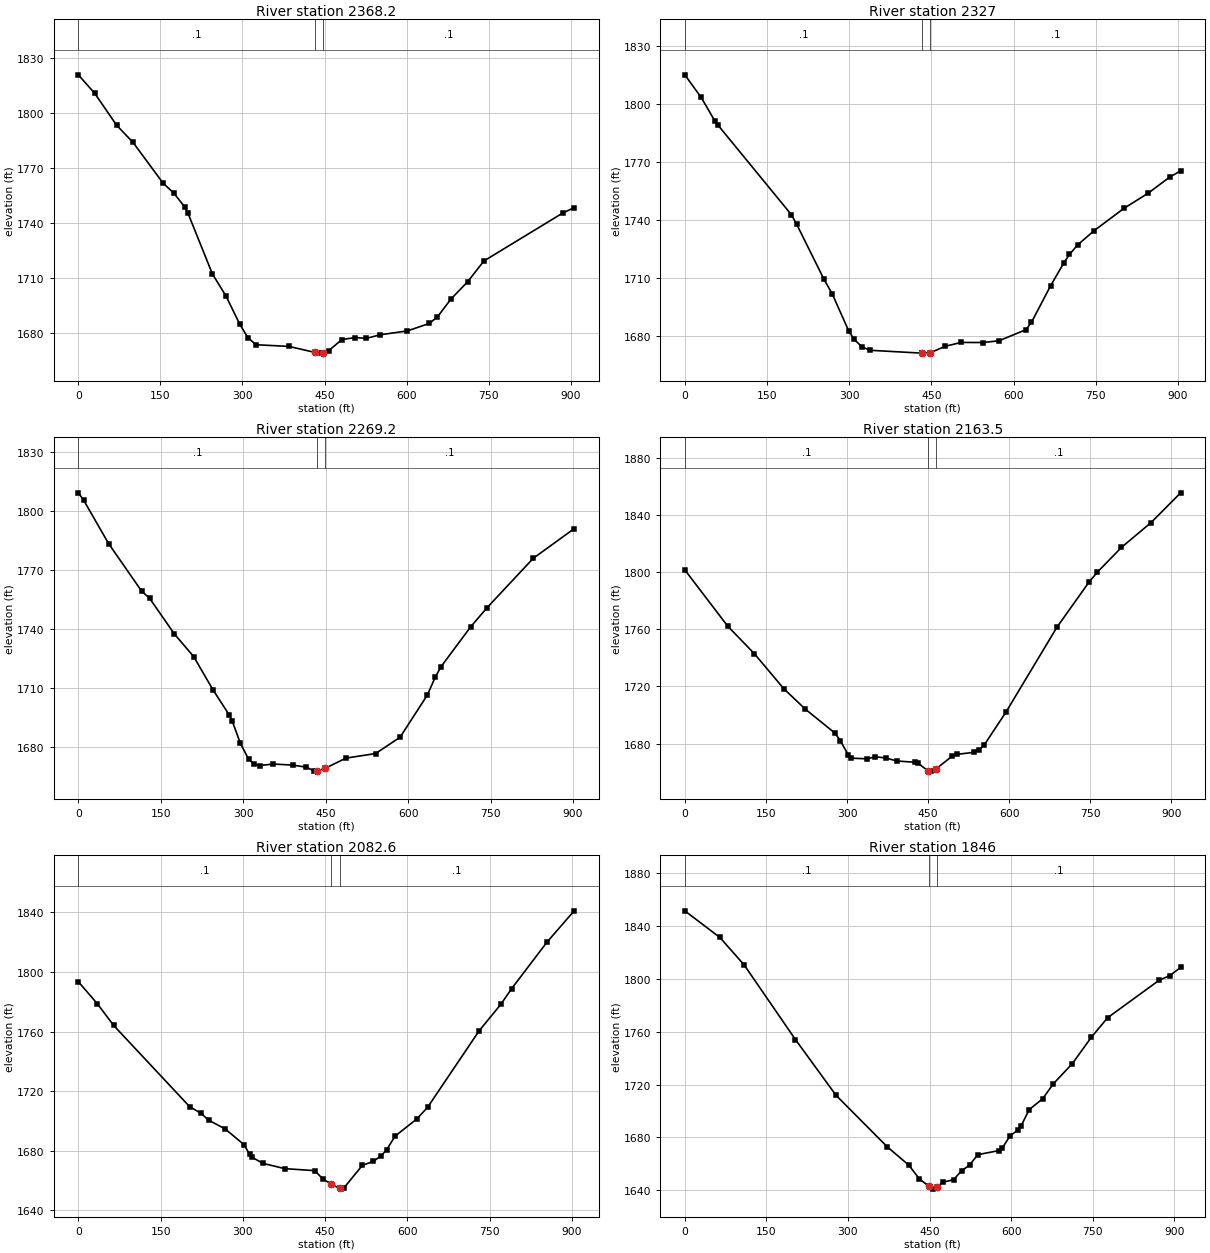
Type RM Length L Ch R = 1 ,2368.2  ,41.4,41.2,40.9
XS GIS Cut Line= 4
     1812179.401      228160.879     1811769.649      228167.478
     1811698.023      228165.302     1811276.357      228114.437
#Sta/Elev= 30
       0 1820.74      30 1810.63      70 1793.24     100 1783.87   154.9 1761.67
   174.9  1756.1   194.9 1748.51   199.9 1745.65   244.9 1712.26   269.9  1700.1
   294.9 1684.83   309.8 1677.46   324.8 1673.56   384.8 1672.65     433 1669.33
   443.2 1668.98     448 1668.98   457.6  1670.3   481.5 1676.35   506.4 1677.49
   526.4 1677.02   551.4 1678.98   601.4 1681.09   641.4 1685.16   656.4 1688.79
   681.3 1698.56   711.3 1707.83   741.3 1719.24   886.2 1745.54   906.2 1748.31
#Mann= 3 , 0 , 0
       0      .1       0     433    .045       0     448      .1       0
Bank Sta=433,448
XS Rating Curve= 0 ,0
Exp/Cntr=0.3,0.1

Type RM Length L Ch R = 1 ,2327    ,58.5,57.8,57.2
XS GIS Cut Line= 4
     1812181.296      228141.095     1811773.268      228126.167
     1811687.571      228124.508     1811280.095      228073.643
#Sta/Elev= 30
       0 1814.86    29.9 1803.16    54.8 1791.05    59.8 1789.12   194.2 1742.69
   204.2  1737.6   253.9 1709.23   268.9 1701.71   298.8 1682.74   308.7 1678.27
   323.6 1674.21   338.6 1672.54   432.1 1671.08   432.9 1671.08   447.9  1671.3
     475 1674.59   503.9 1676.61   543.5 1676.55   573.2 1677.46   622.6 1683.21
   632.5 1687.03   667.2 1705.79   691.9 1717.88   701.8 1722.04   716.6 1726.96
   746.3 1734.24   800.8  1745.8   845.3 1753.68   884.9  1762.1   904.6 1765.21
#Mann= 3 , 0 , 0
       0      .1       0   432.9    .045       0   447.9      .1       0
Bank Sta=432.9,447.9
XS Rating Curve= 0 ,0
Exp/Cntr=0.3,0.1

Type RM Length L Ch R = 1 ,2269.2  ,105.5,105.7,106
XS GIS Cut Line= 4
     1812182.095      228123.587      1811771.24      228067.561
     1811674.916      228068.544     1811286.668       228023.33
#Sta/Elev= 30
       0 1809.07      10 1805.19      55 1783.28   114.9 1759.18   129.9 1755.34
   174.9 1737.22   209.8  1725.8   244.8 1708.96   274.8 1695.98   279.8 1693.08
   294.8  1681.7   309.7 1673.65   319.7 1671.14   329.7 1670.39   354.7 1671.17
   389.7 1670.61   414.7 1669.58   429.1 1667.55   433.8 1667.55   448.8 1668.97
   486.9 1674.17   540.7 1676.49   585.2 1684.77   634.7 1706.17   649.5 1715.48
   659.4 1720.54   713.8 1740.98   743.5 1750.67   827.6  1775.8   901.9 1790.83
#Mann= 3 , 0 , 0
       0      .1       0   433.8    .045       0   448.8      .1       0
Bank Sta=433.8,448.8
XS Rating Curve= 0 ,0
Exp/Cntr=0.3,0.1

Type RM Length L Ch R = 1 ,2163.5  ,67.4,80.9,94.4
XS GIS Cut Line= 4
     1812185.625      228101.243     1811792.864       227962.39
     1811715.215       227962.39      1811297.26      227898.857
#Sta/Elev= 30
       0 1801.51    79.4 1762.14   128.9 1742.78   183.5 1718.22   223.2    1704
   277.7 1687.33   287.6  1682.1   302.5 1671.95   307.5  1669.8   337.2 1669.36
   352.1 1670.78     372 1669.95   391.8 1667.84   426.3 1666.93   431.1 1666.38
   449.6 1660.96   455.4 1660.74   464.6 1662.28   494.2 1671.13   504.2 1672.51
     534 1673.86     544 1675.64   553.9 1679.12   593.7 1701.85   688.2 1761.38
   747.9 1793.13   762.8 1799.84   807.6 1817.24   862.3 1834.58     917 1855.41
#Mann= 3 , 0 , 0
       0      .1       0   449.6    .045       0   464.6      .1       0
Bank Sta=449.6,464.6
XS Rating Curve= 0 ,0
Exp/Cntr=0.3,0.1

Type RM Length L Ch R = 1 ,2082.6  ,242.1,236.6,231
XS GIS Cut Line= 4
     1812199.787      228062.646     1811798.316      227905.581
     1811738.605      227865.359     1811351.724       227759.62
#Sta/Elev= 30
       0 1793.52    34.7  1778.7    64.4 1764.15   203.2 1709.56     223 1705.36
   237.8 1700.53   267.6 1694.72   302.3  1684.1   312.2 1677.65   317.1 1675.57
     337 1671.55   376.6 1668.03   431.1  1666.7   445.5 1661.27   461.6 1657.55
   476.6 1654.78   479.1 1654.29   483.9 1654.92     518 1670.26   537.8 1672.88
   552.6 1676.77   562.5  1680.8   577.4 1689.78     617 1701.31   636.8 1709.13
   730.9 1760.54   770.5 1778.32   790.3 1788.91   854.6 1820.04   904.2 1841.07
#Mann= 3 , 0 , 0
       0      .1       0   461.6    .045       0   476.6      .1       0
Bank Sta=461.6,476.6
XS Rating Curve= 0 ,0
Exp/Cntr=0.3,0.1

Type RM Length L Ch R = 1 ,1846    ,298.2,315.9,334.9
XS GIS Cut Line= 4
     1812296.547      227831.205      1811904.55       227689.36
     1811818.005      227658.043     1811428.823      227553.974
#Sta/Elev= 30
       0 1851.51    64.5 1831.34   109.2 1810.54   203.5 1754.04   277.9 1711.96
   372.2 1672.88   411.9 1659.01   431.4 1648.55   448.9 1643.01   455.6 1640.82
   463.9  1642.7     475 1646.04   494.4 1647.99   508.9 1654.69   523.8 1659.07
   538.8 1666.91   578.5 1670.06   583.5 1671.62   598.4 1681.37   613.4  1685.7
   618.3 1688.54   633.2 1700.95   658.1 1709.27     678 1720.67   712.8  1735.9
   747.6 1755.79   777.5 1770.57     872 1798.86   891.9 1802.48   911.8 1808.66
#Mann= 3 , 0 , 0
       0      .1       0   448.9    .045       0   463.9      .1       0
Bank Sta=448.9,463.9
XS Rating Curve= 0 ,0
Exp/Cntr=0.3,0.1

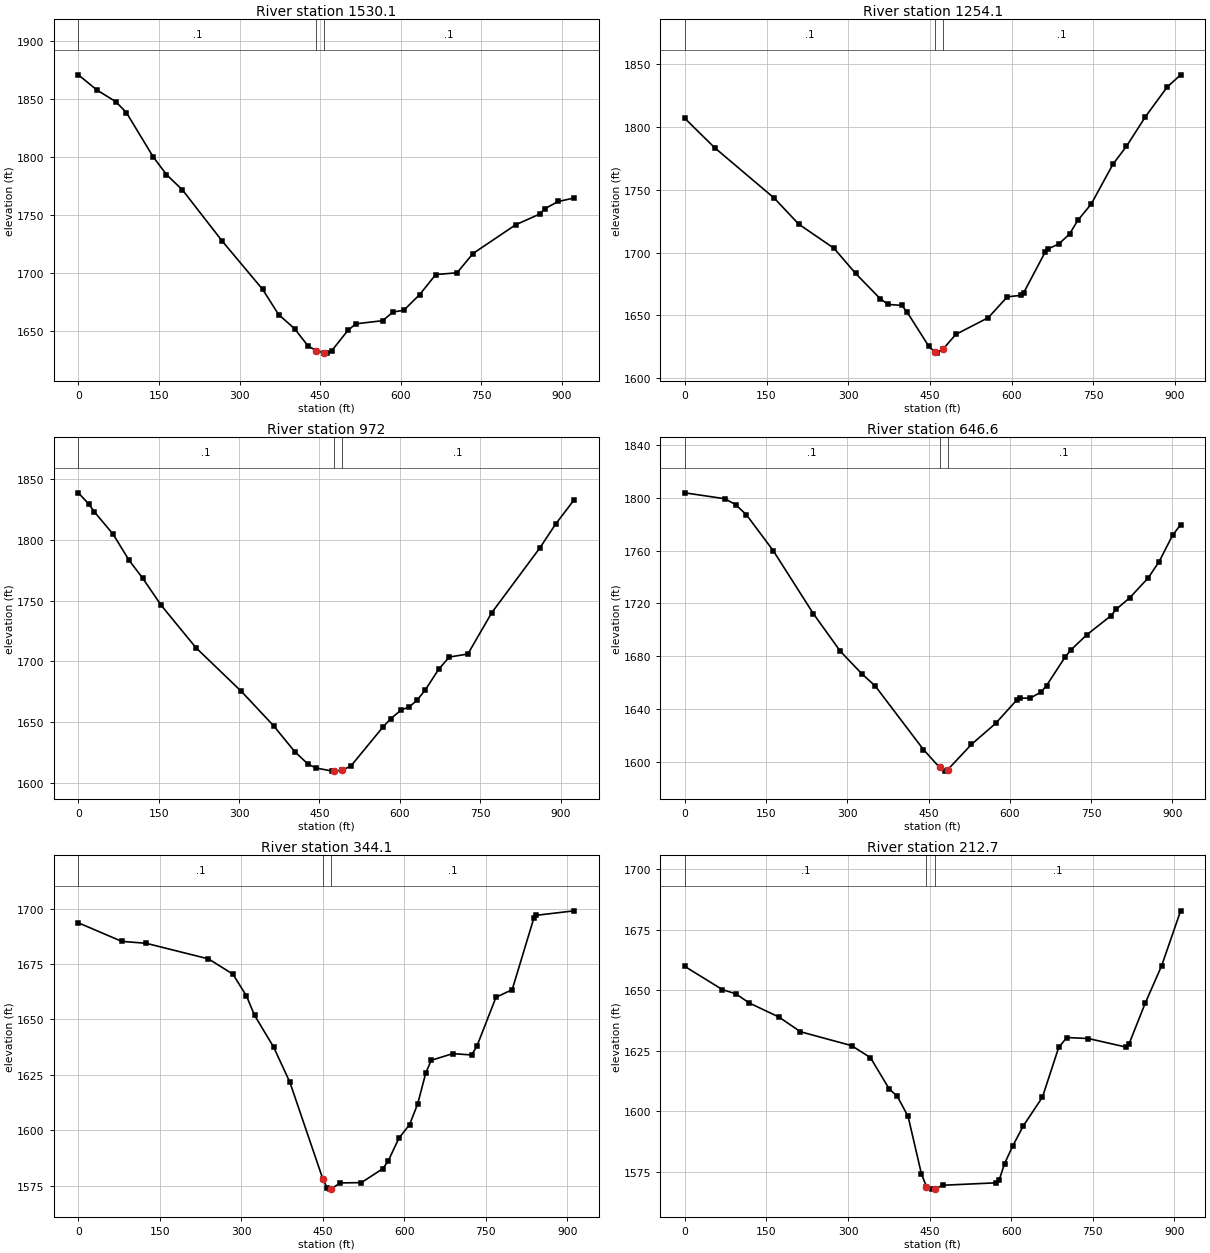
Type RM Length L Ch R = 1 ,1530.1  ,282.4,276.1,268.1
XS GIS Cut Line= 4
     1812337.527      227755.597     1812043.254      227459.568
      1812002.67      227397.289     1811674.915       227117.31
#Sta/Elev= 30
       0  1870.5    34.8 1857.36    69.6 1847.48    89.4 1838.07   139.1 1800.14
     164 1784.78   193.8 1771.56   268.3 1727.26   342.9 1686.18   372.7 1664.48
   402.5 1652.25   427.3 1637.56   442.8 1633.36   457.8 1631.38     462 1631.29
   471.9 1633.48   501.6 1650.77   516.5 1656.51   566.1 1659.14   585.9 1666.65
   605.7 1668.12   635.4 1681.67   665.2 1698.84   704.8 1700.33   734.5 1716.89
   813.8 1741.58   858.4 1750.76   868.3 1755.48   893.1 1761.62   922.8 1764.62
#Mann= 3 , 0 , 0
       0      .1       0   442.8    .045       0   457.8      .1       0
Bank Sta=442.8,457.8
XS Rating Curve= 0 ,0
Exp/Cntr=0.3,0.1

Type RM Length L Ch R = 1 ,1254.1  ,300.5,282.1,263.8
XS GIS Cut Line= 4
     1812526.497      227523.467     1812211.103      227241.433
     1812166.547      227194.736     1811848.786       226916.17
#Sta/Elev= 30
       0 1807.02    54.8  1783.6   164.3 1743.38   209.1 1722.73   273.8 1703.51
   313.6 1683.43   358.4 1663.44   373.3 1658.73   398.2    1658   408.2 1652.56
   447.9  1625.4   459.4  1620.6   462.8 1619.96   474.4 1623.36   497.6  1634.9
   557.2 1648.22     592  1664.8   616.9 1665.99   621.9 1667.91   661.6  1700.5
   666.6    1703   686.5 1706.86   706.4 1714.91   721.3 1725.66   746.2  1738.8
   785.9 1770.41   810.8 1784.73   845.6  1808.3   885.4 1831.85   910.2 1841.66
#Mann= 3 , 0 , 0
       0      .1       0   459.4    .045       0   474.4      .1       0
Bank Sta=459.4,474.4
XS Rating Curve= 0 ,0
Exp/Cntr=0.3,0.1

Type RM Length L Ch R = 1 ,972     ,314.8,325.5,337.3
XS GIS Cut Line= 4
     1812763.757      227144.358     1812370.561      226972.477
     1812290.946      226972.477     1811896.896      226837.223
#Sta/Elev= 30
       0 1838.61      20 1829.14    29.9 1822.94    64.9  1804.6    94.8 1783.08
   119.8 1768.61   154.7 1746.07   219.6 1711.17   304.4 1675.25   364.3 1647.08
   404.2  1625.6   429.1 1615.32     444 1612.29   473.9 1609.72   477.1 1609.72
   492.1 1610.46   508.7 1613.91   568.2 1645.81   583.1 1652.84     603 1660.14
   617.8 1662.51   632.7 1668.37   647.6  1676.5   672.4 1693.39   692.2 1703.54
     727 1706.03   771.6 1740.01   860.9    1793   890.6 1812.75   925.4 1832.88
#Mann= 3 , 0 , 0
       0      .1       0   477.1    .045       0   492.1      .1       0
Bank Sta=477.1,492.1
XS Rating Curve= 0 ,0
Exp/Cntr=0.3,0.1

Type RM Length L Ch R = 1 ,646.6   ,298.8,302.4,304.8
XS GIS Cut Line= 4
     1812905.321      226947.499     1812525.508      226744.484
     1812468.213      226715.976     1812127.077      226469.755
#Sta/Elev= 30
       0 1803.85    74.2 1799.34      94 1794.86   113.8 1787.18   163.4 1759.91
   237.6 1712.04   287.1 1683.74   326.7 1666.66   351.5  1657.4   440.5  1609.2
   470.3 1595.63   479.9  1592.8   485.3 1593.83   529.3 1613.11   573.8 1628.96
   613.4 1646.97   618.4 1648.06   638.2 1648.22     658 1652.88   667.9 1657.73
   702.5 1679.52   712.4 1684.52   742.1 1696.18   786.7 1710.59   796.6 1715.58
   821.3 1724.19     856 1739.54   875.8 1751.77   900.5 1771.64   915.4 1779.68
#Mann= 3 , 0 , 0
       0      .1       0   470.3    .045       0   485.3      .1       0
Bank Sta=470.3,485.3
XS Rating Curve= 0 ,0
Exp/Cntr=0.3,0.1

Type RM Length L Ch R = 1 ,344.1   ,130.3,131.4,132.5
XS GIS Cut Line= 4
     1813017.221      226758.729     1812683.613      226496.616
     1812593.717       226431.24     1812265.839      226244.506
#Sta/Elev= 30
       0 1693.56    79.9 1685.19   124.8 1684.32   239.6 1677.28   284.5 1670.41
   309.5 1660.58   324.4 1651.83   359.4 1637.56   389.3 1621.72   449.8 1578.25
   458.1 1573.94   462.9 1573.46   464.8 1573.48   482.3 1576.26   520.9 1576.39
   560.2 1582.63   570.2 1586.05     590 1596.39   609.9  1602.6   624.8 1612.02
   639.7 1625.97   649.6 1631.55   689.3 1634.57   724.1 1633.95     734 1638.13
   768.8 1659.98   798.6  1663.4   838.3 1695.52   843.2 1696.95   912.7 1698.96
#Mann= 3 , 0 , 0
       0      .1       0   449.8    .045       0   464.8      .1       0
Bank Sta=449.8,464.8
XS Rating Curve= 0 ,0
Exp/Cntr=0.3,0.1

Type RM Length L Ch R = 1 ,212.7   ,211.4,212.3,213.3
XS GIS Cut Line= 4
     1813064.232      226685.666     1812765.356      226397.273
     1812627.572      226285.862     1812362.991      226108.066
#Sta/Elev= 30
       0 1659.84    69.2 1650.26    93.9 1648.52   118.7 1644.72     173 1638.96
   212.6 1632.88   306.6 1627.16   341.2  1622.2   375.8 1609.27   390.6 1606.25
   410.4 1597.93     435 1574.17   444.1 1569.03   454.7 1567.96   459.1 1568.06
   474.4 1569.56   572.8 1570.57   577.8 1571.72   587.6 1578.42   602.5 1585.67
   622.4 1594.14   657.3 1605.89   687.2 1626.42   702.1  1630.5   741.9 1630.08
   811.7 1626.52   816.7 1627.99   846.5 1644.83   876.4 1660.09   911.3 1682.77
#Mann= 3 , 0 , 0
       0      .1       0   444.1    .045       0   459.1      .1       0
Bank Sta=444.1,459.1
XS Rating Curve= 0 ,0
Exp/Cntr=0.3,0.1

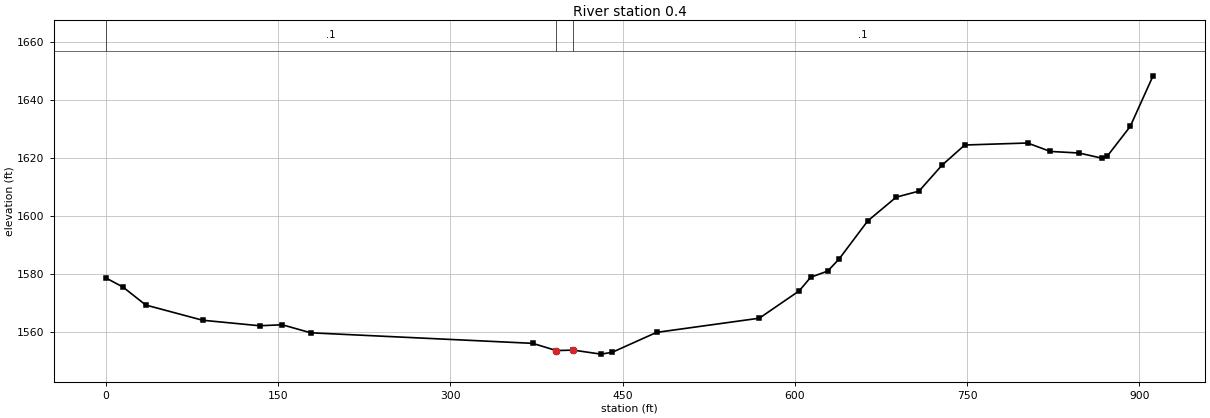
Type RM Length L Ch R = 1 ,0.4     ,1.7,0.4,0
XS GIS Cut Line= 4
     1813176.987      226496.036     1812850.077      226207.422
     1812818.355      226196.693     1812403.502      226043.224
#Sta/Elev= 30
       0 1578.62    14.9 1575.47    34.7 1569.27    84.2 1564.02   133.8 1562.12
   153.6 1562.45   178.4 1559.68   371.7 1556.04   392.1 1553.56   407.1  1553.7
   431.1 1552.32   440.9 1552.95   479.5 1559.82     569 1564.72   603.8 1574.17
   613.7 1578.84   628.6    1581   638.6 1585.21   663.4 1598.29   688.2  1606.5
   708.1  1608.6     728 1617.49   747.9 1624.51   802.6  1625.2   822.4 1622.29
   847.3 1621.75   867.2 1619.98   872.1  1620.7     892 1630.91   911.9 1648.39
#Mann= 3 , 0 , 0
       0      .1       0   392.1    .045       0   407.1      .1       0
Bank Sta=392.1,407.1
XS Rating Curve= 0 ,0
Exp/Cntr=0.3,0.1

Chan Stop Cuts=-1
Use User Specified Reach Order=0